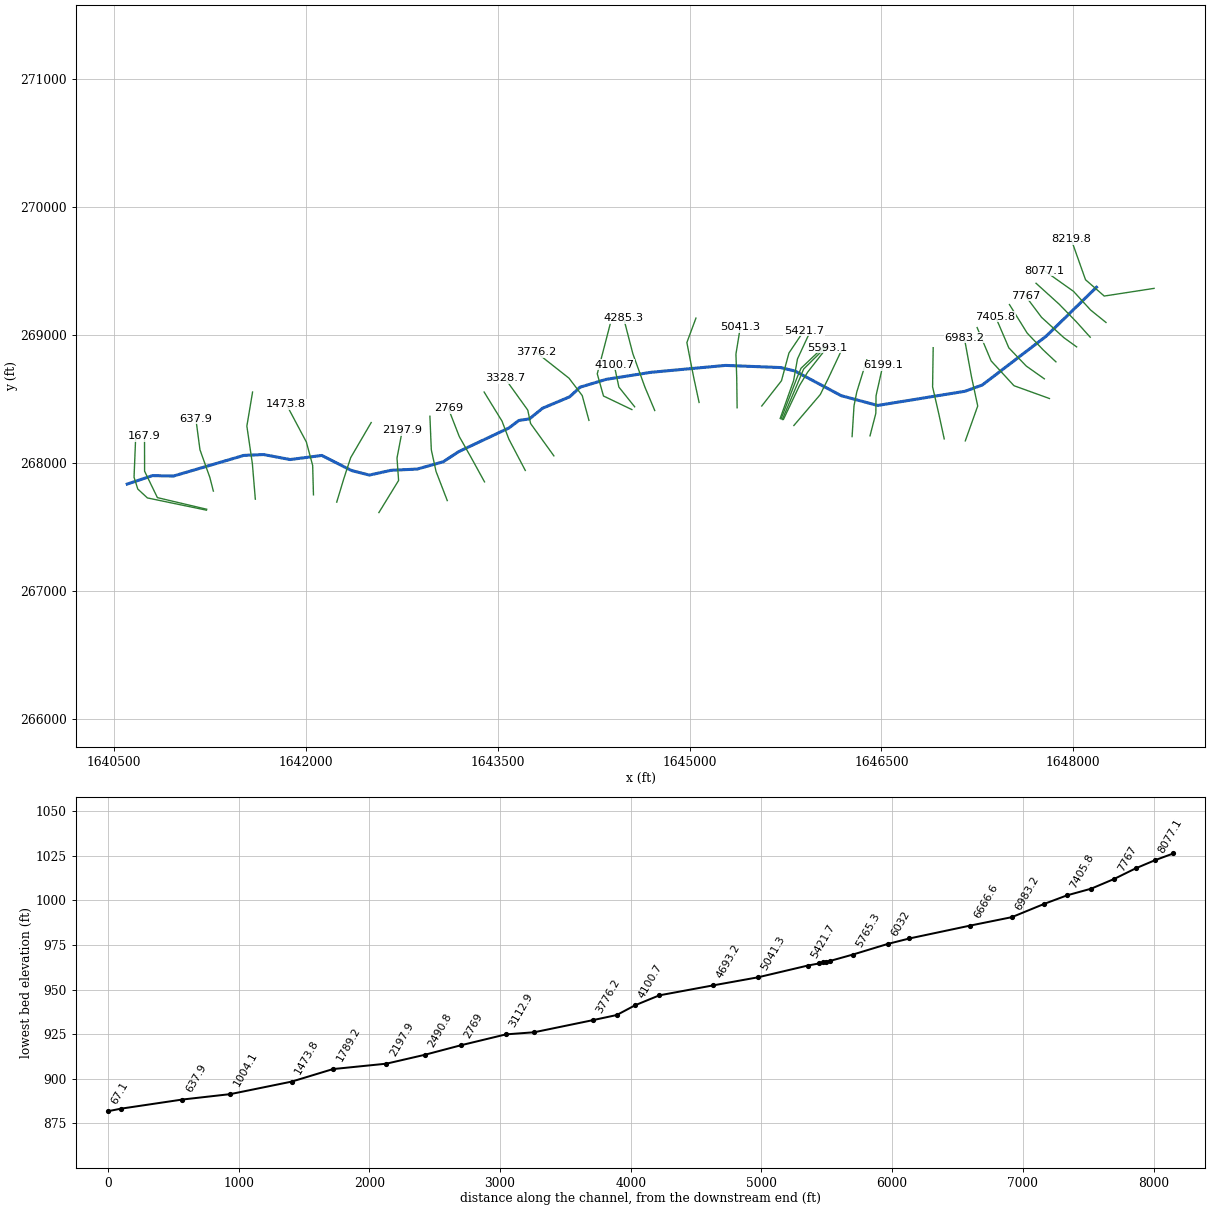
--- lftfrklkcr.prj (project) ---

Proj Title=lftfrklkcr
Current Plan=p01
Default Exp/Contr=0,0
English Units
Geom File=g01
Flow File=f01
Plan File=p01
BEGIN DESCRIPTION:
END DESCRIPTION:
DSS Export Rating Curves= 0
DSS Export Rating Curve Sorted= 0
DSS Export Volume Flow Curves= 0
DXF OffsetX= 0
DXF OffsetY= 0
DXF ScaleX= 0
DXF ScaleY= 0

--- lftfrklkcr.p01 (plan) ---

Plan Title=Floodplain
Program Version=4.00
Geom File=g01
Flow File=f01
K Sum by GR=0
Std Step Tol=0.01
Critical Tol=0.01
Num of Std Step Trials=20
Max Error Tol=0.3
Flow Tol Ratio=0.001
Split Flow NTrial=30
Split Flow Tol=0.02
Split Flow Ratio=0.02
Log Output Level=0
Friction Slope Method=1
Unsteady Friction Slope Method=2
Unsteady Bridges Friction Slope Method=1
Global Log Level=0
CheckData=False
Run HTab=0
Run UNet=0
Run PostProcess=0
UNET Theta=0
UNET Theta Warmup=0
UNET ZTol=0
UNET ZSATol=0
UNET MxIter=0
UNET MaxInSteps=0
UNET DtIC=0
UNET DtMin=0
UNET MaxCRTS=0
UNET WFStab=0
UNET SFStab=0
UNET WFX=0
UNET SFX=0
UNET DSS MLevel=0
UNET DZMax Abort=0
UNET Convert EG Bridges=0
UNET Use Existing IB Tables=0
UNET Froude Limit=0
UNET Froude Power=0
Write IC File=0
Echo Input=False
Echo Output=False
Write Detailed=0

--- lftfrklkcr.f01 (steady flow) ---

Flow Title=NFF Regression Equation
Program Version=4.00
Number of Profiles= 1
Profile Names=P100yr
River Rch & RM=lftfrklkcr,Main            ,8219.8
     368
River Rch & RM=lftfrklkcr,Main            ,6983.2
     389
River Rch & RM=lftfrklkcr,Main            ,6666.6
     588
River Rch & RM=lftfrklkcr,Main            ,4285.3
     633
River Rch & RM=lftfrklkcr,Main            ,4100.7
     706
River Rch & RM=lftfrklkcr,Main            ,3776.2
     706
River Rch & RM=lftfrklkcr,Main            ,3328.7
     796
River Rch & RM=lftfrklkcr,Main            ,167.9
     850
Boundary for River Rch & Prof#=lftfrklkcr,Main            , 1
Up Type= 0
Dn Type= 3
Dn Slope=0.016
DSS Import GetInterval= 0
DSS Import GetPeak= 0
DSS Import FillOption= 0

--- lftfrklkcr.g01 (geometry) ---

Geom Title=USGS 10m DEM
Program Version=4.00

River Reach=lftfrklkcr      ,Main
Reach XY= 30
      1648182.38       269374.11     1647788.384      268990.751
     1647289.444      268609.327     1647154.205      268560.219
     1646470.519      268449.142     1646186.051      268525.449
     1645823.341      268718.569     1645711.379      268745.617
     1645280.902      268762.456     1644698.333       268708.49
     1644347.247      268653.236     1644142.825      268591.977
     1644061.673      268516.712     1643850.127      268427.704
     1643747.203      268344.341     1643663.655      268331.557
     1643588.387      268273.865     1643193.696      268087.822
     1643072.637      268008.527     1642868.937       267951.42
     1642664.214      267941.882     1642495.421      267904.621
     1642355.247      267940.207     1642123.228      268058.165
     1641875.467      268026.081     1641667.894      268065.118
     1641513.437      268058.394     1640963.296      267897.112
     1640798.921      267900.281     1640601.554      267834.201

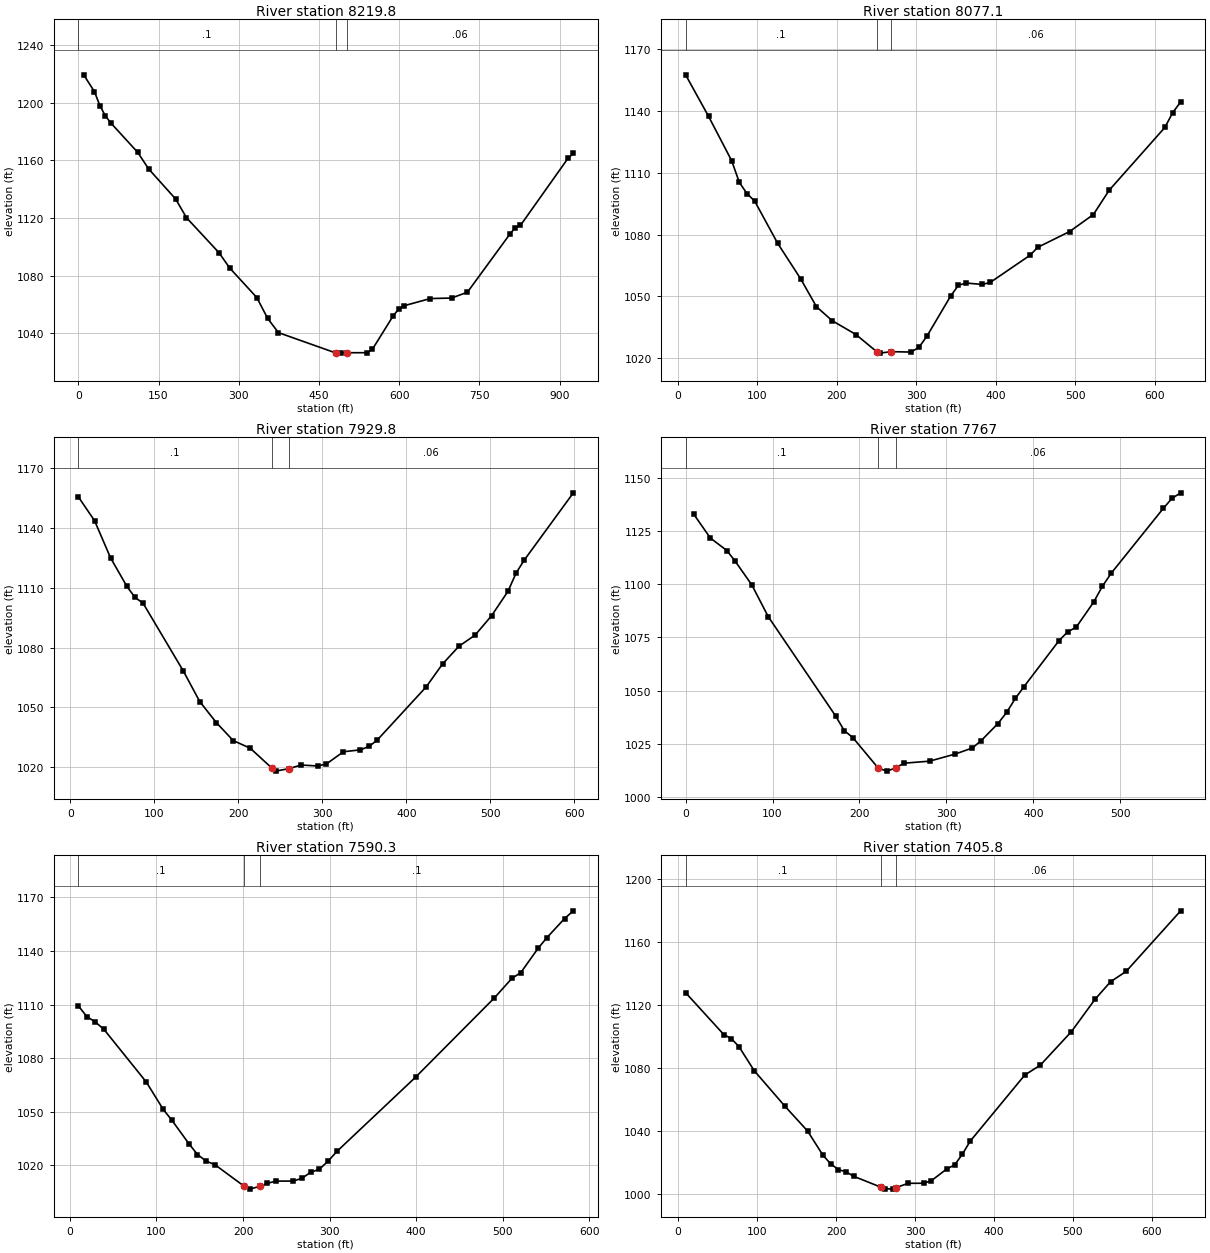
Type RM Length L Ch R = 1 ,8219.8  ,145.5,142.7,139.9
XS GIS Cut Line= 4
     1648632.631      269364.992     1648242.755      269304.936
     1648096.298      269432.805     1647983.792      269750.289
#Sta/Elev= 30
    10.1 1219.33    30.3 1207.61    40.5  1197.8    50.6 1190.96    60.7    1186
   111.3  1165.5   131.5  1154.1   182.1  1133.2   202.3 1120.28     263 1096.05
   283.2 1085.37   333.8 1064.91     354 1050.51   374.2 1040.61   481.7 1026.48
   491.7 1026.39   501.7 1026.68   540.3 1026.68     550 1029.09   588.9 1052.28
   598.8 1056.83   608.7  1059.2   658.2 1064.22   697.9 1064.58   727.6 1068.62
   806.8 1108.78   816.8 1113.29   826.7 1114.89   915.8 1161.52   925.7 1164.82
#Mann= 3 , 0 , 0
       0      .1       0   481.7    .045       0   501.7     .06       0
Bank Sta=481.7,501.7
XS Rating Curve= 0 ,0
Exp/Cntr=0.3,0.1

Type RM Length L Ch R = 1 ,8077.1  ,146.5,147.3,148.1
XS GIS Cut Line= 4
     1648256.582      269098.367     1648136.369      269195.462
     1648002.286      269341.875     1647774.191      269503.699
#Sta/Elev= 30
     9.7  1157.4    38.6 1137.27    67.6 1115.83    77.3 1105.29    86.9 1099.85
    96.6 1096.23   125.6 1075.72   154.5 1058.54   174.4 1045.01   194.2 1038.25
     224 1031.55  249.95 1023.31   253.8 1022.53  268.77 1023.24   293.5 1023.04
   303.4 1025.38   313.4 1030.75   343.1  1050.1   353.1 1055.46     363  1056.5
     383  1055.8     393 1056.78     443 1069.92   452.9 1073.82   492.9 1081.44
   522.9 1089.71   542.8  1101.5   612.8 1131.89   622.7 1139.09   632.7 1144.26
#Mann= 3 , 0 , 0
     9.7      .1       0  249.95    .045       0  268.77     .06       0
Bank Sta=249.95,268.77
XS Rating Curve= 0 ,0
Exp/Cntr=0.3,0.1

Type RM Length L Ch R = 1 ,7929.8  ,161.4,162.8,164.3
XS GIS Cut Line= 4
     1648133.287      268982.778     1648023.863      269104.532
      1647889.78      269241.698      1647709.46      269405.063
#Sta/Elev= 30
     9.6 1155.64    28.9 1143.68    48.1 1124.91    67.4 1110.71      77 1105.18
    86.7 1102.24   134.8 1068.08   154.1 1052.91   173.8 1042.37     194  1033.3
   214.2 1029.48  239.95 1019.52   244.5 1017.98  260.15 1019.23   274.8 1021.04
   294.9 1020.55     305 1021.62   325.2 1027.71   345.4 1028.66   355.5 1030.36
   365.2 1033.48   423.6 1060.23   443.1 1071.73   462.6 1080.62     482 1086.29
   501.5 1095.98     521 1108.21   530.7 1117.43   540.4  1123.9   598.8 1157.62
#Mann= 3 , 0 , 0
     9.6      .1       0  239.95    .045       0  260.15     .06       0
Bank Sta=239.95,260.15
XS Rating Curve= 0 ,0
Exp/Cntr=0.3,0.1

Type RM Length L Ch R = 1 ,7767    ,178.4,176.7,175
XS GIS Cut Line= 4
     1648026.945       268907.26     1647926.768      268979.696
     1647752.614      269138.438     1647626.237      269306.427
#Sta/Elev= 30
     9.5 1132.83    28.5 1121.69    47.5 1115.81    57.1 1110.77    76.1 1099.71
    95.1 1084.71   172.7 1037.95   182.5 1031.14   192.4 1027.85   221.6 1013.51
   231.6 1012.09   241.6  1013.6   251.3 1015.82   280.7 1016.78   310.2 1020.13
   329.8 1022.96   339.6 1026.25   359.3 1034.45   369.3 1039.71   379.3 1046.25
   389.3 1051.84   429.3 1073.31   439.4 1077.55   449.4  1079.8   469.4 1091.57
   479.4 1098.96   489.4 1105.04   549.5 1135.63   559.5 1140.36   569.5 1142.96
#Mann= 3 , 0 , 0
       0      .1       0   221.6    .045       0   241.6     .06       0
Bank Sta=221.6,241.6
XS Rating Curve= 0 ,0
Exp/Cntr=0.3,0.1

Type RM Length L Ch R = 1 ,7590.3  ,184.4,184.4,184.5
XS GIS Cut Line= 4
     1647865.121       268790.13     1647764.943      268884.142
     1647640.107      269015.143       1647501.4      269238.615
#Sta/Elev= 30
     9.8 1109.29    19.6 1103.28    29.4 1100.21    39.3 1096.14    88.3 1066.59
   107.9 1051.24   117.8 1045.23   137.4 1032.12   147.4    1026   157.5 1022.29
   167.5 1020.31  201.18 1008.28   207.8 1006.61     220 1008.26   227.9 1009.83
   237.9  1011.1     258 1011.13   268.1 1012.72   278.1 1016.04   288.2 1017.75
   298.2 1022.28   308.3 1027.69   399.3 1069.33   490.3 1113.75   510.5 1124.65
   520.7 1127.86   540.9  1141.6     551 1147.52   571.2  1158.1   581.4 1162.46
#Mann= 3 , 0 , 0
     9.8      .1       0  201.18    .045       0     220      .1       0
Bank Sta=201.18,220
XS Rating Curve= 0 ,0
Exp/Cntr=0.3,0.1

Type RM Length L Ch R = 1 ,7405.8  ,174.1,173.6,173.2
XS GIS Cut Line= 4
     1647774.191      268657.588     1647632.401      268757.765
     1647496.777      268899.554     1647391.976      269144.603
#Sta/Elev= 30
     9.6 1127.82    57.9  1101.2    67.5 1098.61    77.2 1093.48    96.4 1078.24
     135  1055.8     164 1039.84   183.4 1024.49   193.2 1018.99     203 1015.32
   212.8 1013.83   222.7 1010.98   256.5 1004.18   261.9  1003.2   271.7 1002.88
  276.23 1003.88   291.3 1006.57     311 1006.63   320.8 1008.28   340.4 1015.77
   350.2 1018.28     360 1025.11   369.8 1033.33   438.9 1075.41   458.7 1081.76
   498.1  1103.1   527.8 1123.55   547.5 1134.75   567.2 1141.31   636.3 1179.87
#Mann= 3 , 0 , 0
     9.6      .1       0   256.5    .045       0  276.23     .06       0
Bank Sta=256.5,276.23
XS Rating Curve= 0 ,0
Exp/Cntr=0.3,0.1

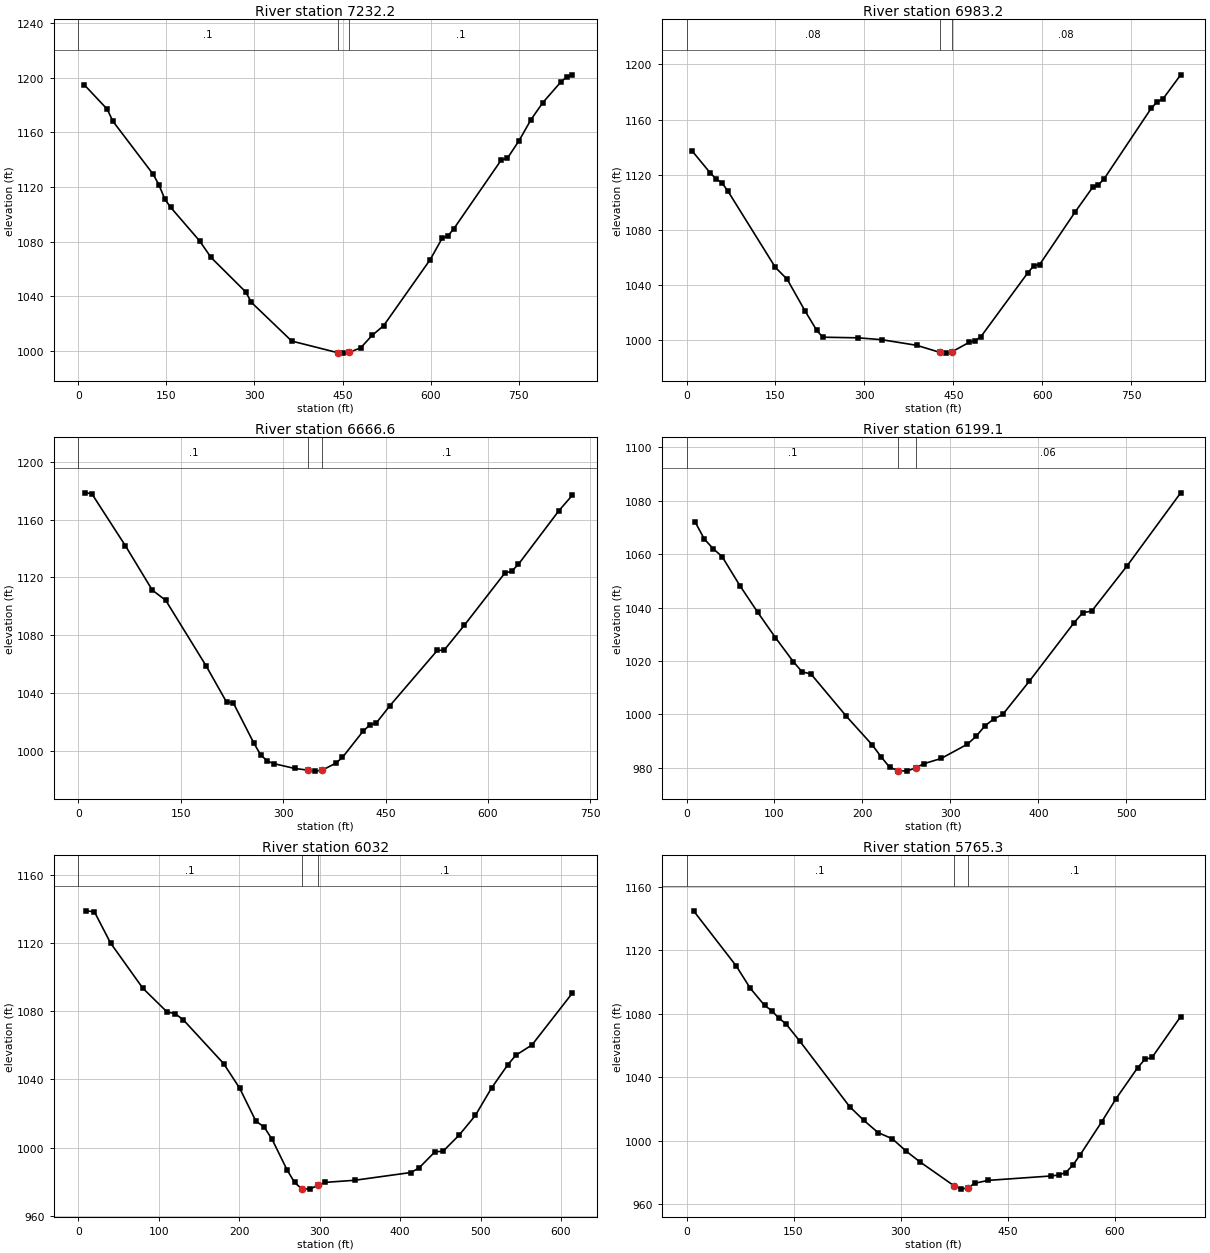
Type RM Length L Ch R = 1 ,7232.2  ,262.7,249,235.4
XS GIS Cut Line= 4
     1647814.261      268503.469     1647536.848      268603.646
      1647358.07      268797.836     1647248.646      269058.296
#Sta/Elev= 30
     9.8 1195.18    49.2 1177.12      59 1168.24   127.8 1129.18   137.6 1121.34
   147.5 1111.01   157.3 1105.09   206.5 1080.52   226.1  1068.3   285.1 1043.02
   294.9 1035.31   363.4 1006.98   441.4  998.48   451.4  998.12   461.4  998.76
   480.7 1001.93   500.2 1011.09   519.8 1018.19   599.3 1066.79   619.4 1082.28
   629.5 1084.16   639.6  1089.5   720.3  1139.9   730.4 1140.95   750.6 1154.06
   770.8 1169.44     791 1181.95   821.2 1196.82   831.3 1200.73   841.4  1202.3
#Mann= 3 , 0 , 0
       0      .1       0   441.4    .045       0   461.4      .1       0
Bank Sta=441.4,461.4
XS Rating Curve= 0 ,0
Exp/Cntr=0.3,0.1

Type RM Length L Ch R = 1 ,6983.2  ,316.1,316.5,317
XS GIS Cut Line= 4
     1647156.175      268172.114     1647253.269      268444.904
     1647203.951      268676.082     1647148.469      268978.155
#Sta/Elev= 30
      10 1137.01    39.9  1121.4    49.9 1116.97    59.9 1114.11    69.9 1108.08
   149.8 1052.82   169.7 1044.21   199.7 1021.33   219.7 1007.06   229.6  1002.2
   289.6 1001.73     329 1000.39     388  996.31   427.3  991.17   437.3  990.64
   447.3  991.56   476.7   998.5   486.5  999.66   496.4 1002.64   575.5 1048.99
   585.4 1054.01   595.3 1054.87   654.7 1092.76   684.5 1110.81   694.4  1112.7
   704.3 1117.26   783.5 1168.29   793.4 1172.91   803.3  1175.1   833.1  1192.5
#Mann= 3 , 0 , 0
       0     .08       0   427.3    .045       0   447.3     .08       0
Bank Sta=427.3,447.3
XS Rating Curve= 0 ,0
Exp/Cntr=0.3,0.1

Type RM Length L Ch R = 1 ,6666.6  ,473.4,467.5,461.6
XS GIS Cut Line= 4
     1646991.268      268187.526     1646949.655      268380.174
     1646900.337      268594.399     1646904.961      268901.095
#Sta/Elev= 30
     9.9 1178.51    19.7    1178      69 1141.92   108.4 1111.22   128.1  1104.1
   187.2 1058.81   217.1 1033.77   227.1 1033.13     257 1005.47     267   997.3
     277  992.83     287  991.08     317  987.79     337  986.59     347  985.95
     357  986.61     377  991.38   386.9  995.44   416.9 1013.46   426.8 1017.81
   436.7 1019.42   456.5 1031.29   525.8 1069.49   535.7 1069.59   565.3 1086.85
   624.7    1123   634.6 1124.24   644.5 1129.01   703.9 1166.18   723.7 1176.93
#Mann= 3 , 0 , 0
       0      .1       0     337    .045       0     357      .1       0
Bank Sta=337,357
XS Rating Curve= 0 ,0
Exp/Cntr=0.3,0.1

Type RM Length L Ch R = 1 ,6199.1  ,171.8,167.1,162.4
XS GIS Cut Line= 4
     1646410.905      268211.734     1646456.476       268387.88
     1646458.017      268525.046     1646511.082      268761.938
#Sta/Elev= 30
    10.1 1071.86    20.2 1065.69    30.3 1062.04    40.4 1059.11    60.6 1048.24
    80.9 1038.24   101.1 1028.72   121.3 1019.76   131.4 1015.91   141.5 1015.09
   181.9  999.19   211.3  988.47   221.1  984.11   230.9  980.17   240.5  978.87
   250.5  978.69   260.5  979.92   270.1  981.48   289.7  983.46   319.1  988.73
   329.2   991.7   339.3  995.64   349.5  998.25   359.6  999.94   389.9 1012.42
   440.5 1034.24   450.6 1038.06   460.7 1038.64   501.2 1055.72   561.9 1082.97
#Mann= 3 , 0 , 0
       0      .1       0   240.5    .045       0   260.5     .06       0
Bank Sta=240.5,260.5
XS Rating Curve= 0 ,0
Exp/Cntr=0.3,0.1

Type RM Length L Ch R = 1 ,6032    ,273.3,266.8,260.2
XS GIS Cut Line= 4
     1646270.753      268205.636      1646285.78      268446.061
     1646307.742       268555.87     1646385.186      268805.543
#Sta/Elev= 30
      10  1138.8    20.1 1138.21    40.1 1119.96    80.3  1093.4   110.4 1079.47
   120.4 1078.51   130.5 1074.93   180.7 1049.21   200.7 1034.74   220.8 1015.42
   230.9 1012.12   240.9 1004.85   259.6  986.83   268.9  979.51   277.6  975.85
   287.6  975.59   297.6  977.74   306.2  979.53   343.5  980.77   413.2  985.32
   423.3  987.87   443.4   997.5   453.4  997.78   473.5 1007.29   493.6 1018.81
   513.7 1034.86   533.9 1048.51   543.9  1054.1     564 1060.15   614.3 1090.61
#Mann= 3 , 0 , 0
       0      .1       0   277.6    .045       0   297.6      .1       0
Bank Sta=277.6,297.6
XS Rating Curve= 0 ,0
Exp/Cntr=0.3,0.1

Type RM Length L Ch R = 1 ,5765.3  ,174.3,172.1,170
XS GIS Cut Line= 4
     1645815.342      268292.326     1646021.861      268534.293
      1646085.05      268662.211     1646183.686      268871.812
#Sta/Elev= 30
     9.9 1144.94    69.6 1110.24    89.5 1096.07   109.4 1085.36   119.3 1082.11
   129.2 1077.39   139.2 1073.81   159.1 1062.65   228.6 1021.56   248.5 1012.91
   268.4 1005.24   288.3 1001.36   308.2  993.38   327.6  986.62   374.7  971.77
   384.7  969.63   394.7  970.46   403.7  973.31   422.7  975.14   511.1  977.93
   521.2  978.54   531.3  980.03   541.4  984.81   551.4  991.14   581.7    1012
   601.8 1026.59     632 1046.07   642.1 1051.35   652.2 1052.55   692.4 1078.37
#Mann= 3 , 0 , 0
       0      .1       0   374.7    .045       0   394.7      .1       0
Bank Sta=374.7,394.7
XS Rating Curve= 0 ,0
Exp/Cntr=0.3,0.1

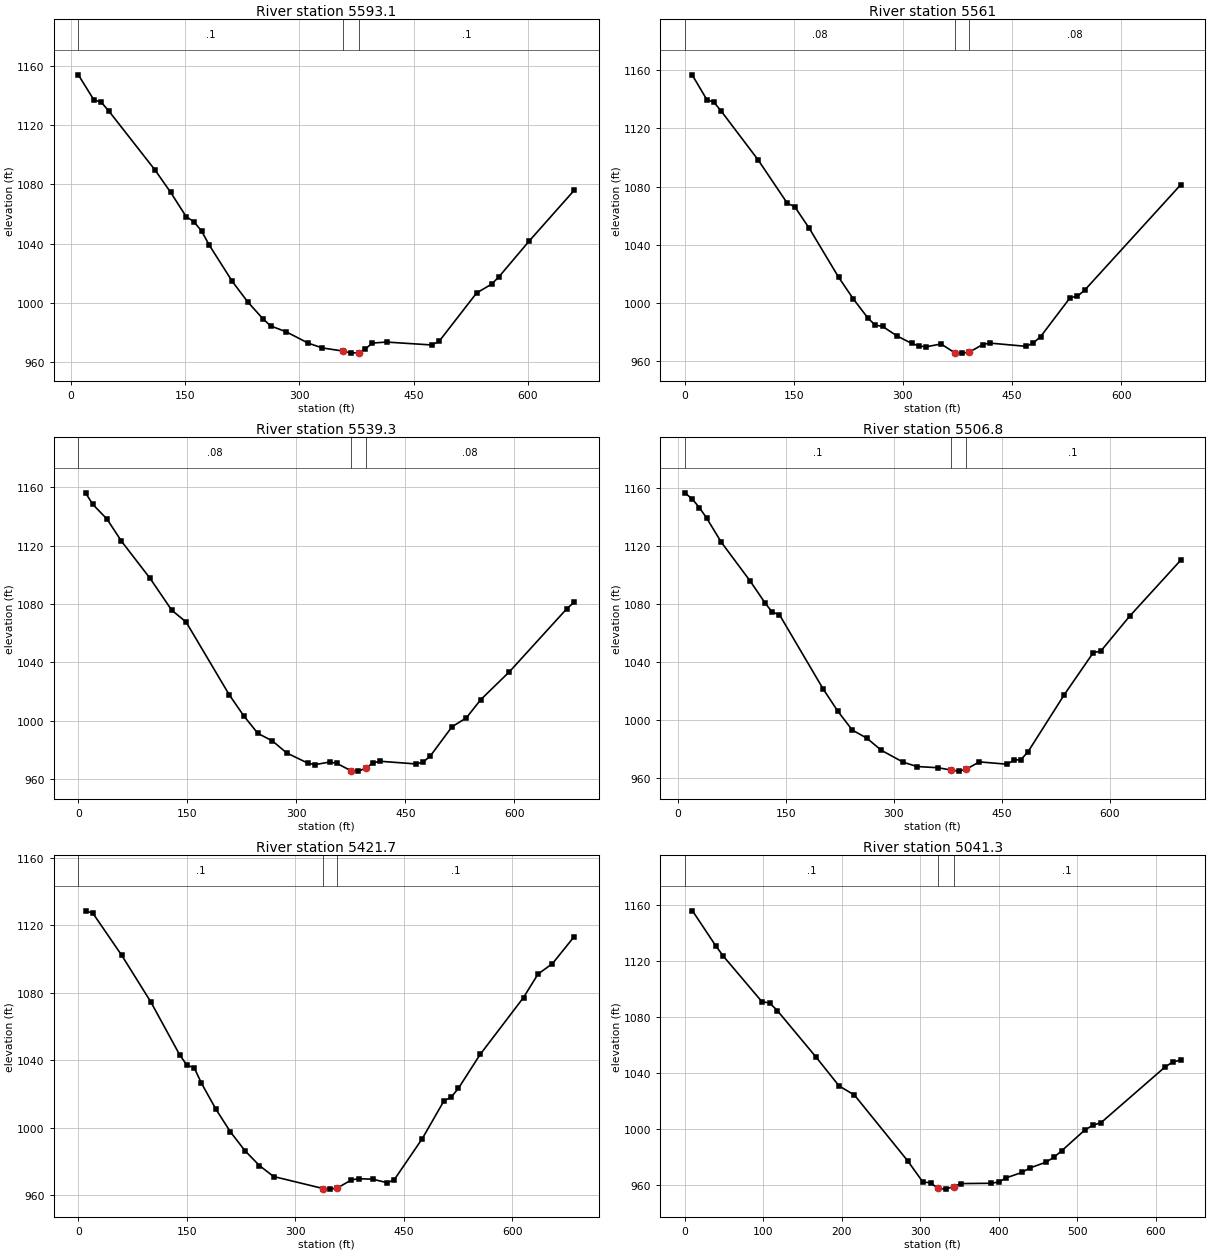
Type RM Length L Ch R = 1 ,5593.1  ,28.3,32.1,35.9
XS GIS Cut Line= 4
     1645733.761      268339.933     1645859.247      268604.559
     1645922.315      268708.589     1646073.809      268902.345
#Sta/Elev= 30
    10.1 1153.74    30.3 1136.98    40.4 1135.16    50.5 1129.09   111.1 1089.29
   131.3 1074.42   151.5 1058.16   161.6 1054.71   171.7 1048.49   181.8 1038.96
   212.1 1014.43   232.3 1000.63   252.5  989.11   262.6   984.4   282.8  980.49
   311.6  972.84   330.3  969.59   357.7  967.49   367.7  966.11   377.7  966.48
   386.5   968.9   395.8  972.89   414.5  973.57   473.6  971.61   483.4   974.1
   532.6  1006.7   552.3 1012.64   562.1 1017.73   601.4 1041.62   660.5 1075.86
#Mann= 3 , 0 , 0
    10.1      .1       0   357.7    .045       0   377.7      .1       0
#XS Ineff= 2 , 0
       0     339             386       0
Permanent Ineff=
       F       F
Bank Sta=357.7,377.7
XS Rating Curve= 0 ,0
Exp/Cntr=0.3,0.1

Type RM Length L Ch R = 1 ,5561    ,22,21.7,21.5
XS GIS Cut Line= 4
     1645724.658      268339.282     1645862.498      268663.726
     1645891.756      268733.947     1646071.858      268912.098
#Sta/Elev= 30
    10.1 1156.63    30.2 1139.67    40.3  1137.7    50.4 1131.52   100.7 1098.37
     141 1068.51   151.1 1066.24   171.2 1051.34   211.5 1017.81   231.6 1003.01
   251.8   989.8   261.9  984.91   271.9  984.09   292.1  977.44   312.2  972.36
   322.3  970.58   332.4  970.11   352.5  972.01     371  966.05     381  965.73
     391  966.39   409.6  971.55   419.1  972.64   469.1  970.39   479.2   972.6
   489.4   977.1   529.9 1003.74     540 1004.75   550.2 1009.06   681.9 1081.15
#Mann= 3 , 0 , 0
       0     .08       0     371    .045       0     391     .08       0
Bank Sta=371,391
XS Rating Curve= 0 ,0
Exp/Cntr=0.3,0.1

Type RM Length L Ch R = 1 ,5539.3  ,26.5,32.5,38.4
XS GIS Cut Line= 4
     1645715.555      268345.134     1645844.292       268676.73
       1645871.6      268740.449     1646058.204        268917.3
#Sta/Elev= 30
     9.9 1156.28    19.8 1148.39    39.5 1138.22    59.3  1123.1    98.8 1097.52
   128.5 1075.72   148.2 1067.66   207.5 1017.77   227.3 1003.43     247  991.17
   266.8  986.09   286.5  977.82   316.2  970.64   326.1  969.75   345.8  971.56
   355.7   970.6   375.4  965.47   385.4  965.29   395.4  967.32   405.2   970.9
   415.1  972.06   464.6  970.22   474.5  971.49   484.4  975.79     514  995.71
   533.8 1001.85   553.6 1014.36   593.1 1033.52   672.2 1076.86   682.1 1081.18
#Mann= 3 , 0 , 0
       0     .08       0   375.4    .045       0   395.4     .08       0
Bank Sta=375.4,395.4
XS Rating Curve= 0 ,0
Exp/Cntr=0.3,0.1

Type RM Length L Ch R = 1 ,5506.8  ,87.5,85.1,82.7
XS GIS Cut Line= 4
     1645708.403      268347.735     1645813.083       268642.92
     1645843.642       268813.27     1645932.718      269005.725
#Sta/Elev= 30
    10.1 1156.64    20.2 1152.48    30.3 1146.47    40.4 1139.25    60.6 1122.69
     101 1095.67   121.2 1080.91   131.3 1074.38   141.4 1072.63   202.1 1021.38
   222.3 1006.16   242.5  993.03   262.7  987.44   282.9  979.05   313.2  970.85
   332.4  967.85   361.3  967.03   380.1  965.42   390.1  964.68   400.1  965.84
     419  971.05   457.4  969.45     467  972.25   476.7  972.68   486.3  977.87
   536.8  1017.4   577.2 1046.49   587.3 1047.34   627.6 1071.59   698.3 1110.09
#Mann= 3 , 0 , 0
    10.1      .1       0   380.1    .045       0   400.1      .1       0
#XS Ineff= 2 , 0
       0     361             402       0
Permanent Ineff=
       F       F
Bank Sta=380.1,400.1
XS Rating Curve= 0 ,0
Exp/Cntr=0.3,0.1

Type RM Length L Ch R = 1 ,5421.7  ,373,380.4,387.9
XS GIS Cut Line= 4
     1645564.129      268444.904     1645718.247      268642.176
     1645776.812      268859.483     1645893.943      269033.637
#Sta/Elev= 30
      10 1128.49      20 1127.13    60.1 1102.03   100.1 1074.54   140.2 1043.02
   150.2 1036.92   160.2 1035.44   170.2 1026.25   190.3 1010.77   210.3  997.39
   230.3  986.28   250.3  977.46   269.9  970.97   338.2  963.87   348.2   963.5
   358.2  964.23   377.5  968.97   387.3  969.66   406.9   969.4   426.5  967.33
   436.3  968.86   475.4  993.45   505.4 1015.87   515.4 1018.02   525.4 1023.32
   555.4 1043.36   615.3  1077.1   635.3 1090.98   655.3 1097.19   685.3 1113.19
#Mann= 3 , 0 , 0
       0      .1       0   338.2    .045       0   358.2      .1       0
Bank Sta=338.2,358.2
XS Rating Curve= 0 ,0
Exp/Cntr=0.3,0.1

Type RM Length L Ch R = 1 ,5041.3  ,344.1,348.1,352.1
XS GIS Cut Line= 4
      1645371.48      268431.033     1645368.398      268666.835
     1645362.233      268850.236     1645396.139      269059.837
#Sta/Elev= 30
     9.8 1155.82    39.3 1130.91    49.1 1123.42    98.3 1090.84   108.1 1090.01
   117.9  1084.5     167 1051.43   196.5 1030.72   216.2  1024.1   284.1  977.05
   303.4   961.9   313.1  961.56   322.4  957.37   332.4  956.92   342.4  958.77
   351.7  960.88   390.4  961.11     400  962.03   409.7  965.03   429.4  968.82
   439.5  972.02   459.8  976.07   469.9  979.54     480  984.22   510.3  999.52
   520.4 1002.58   530.5 1004.51   611.4 1043.99   621.5 1047.76   631.7 1049.14
#Mann= 3 , 0 , 0
       0      .1       0   322.4    .045       0   342.4      .1       0
Bank Sta=322.4,342.4
XS Rating Curve= 0 ,0
Exp/Cntr=0.3,0.1

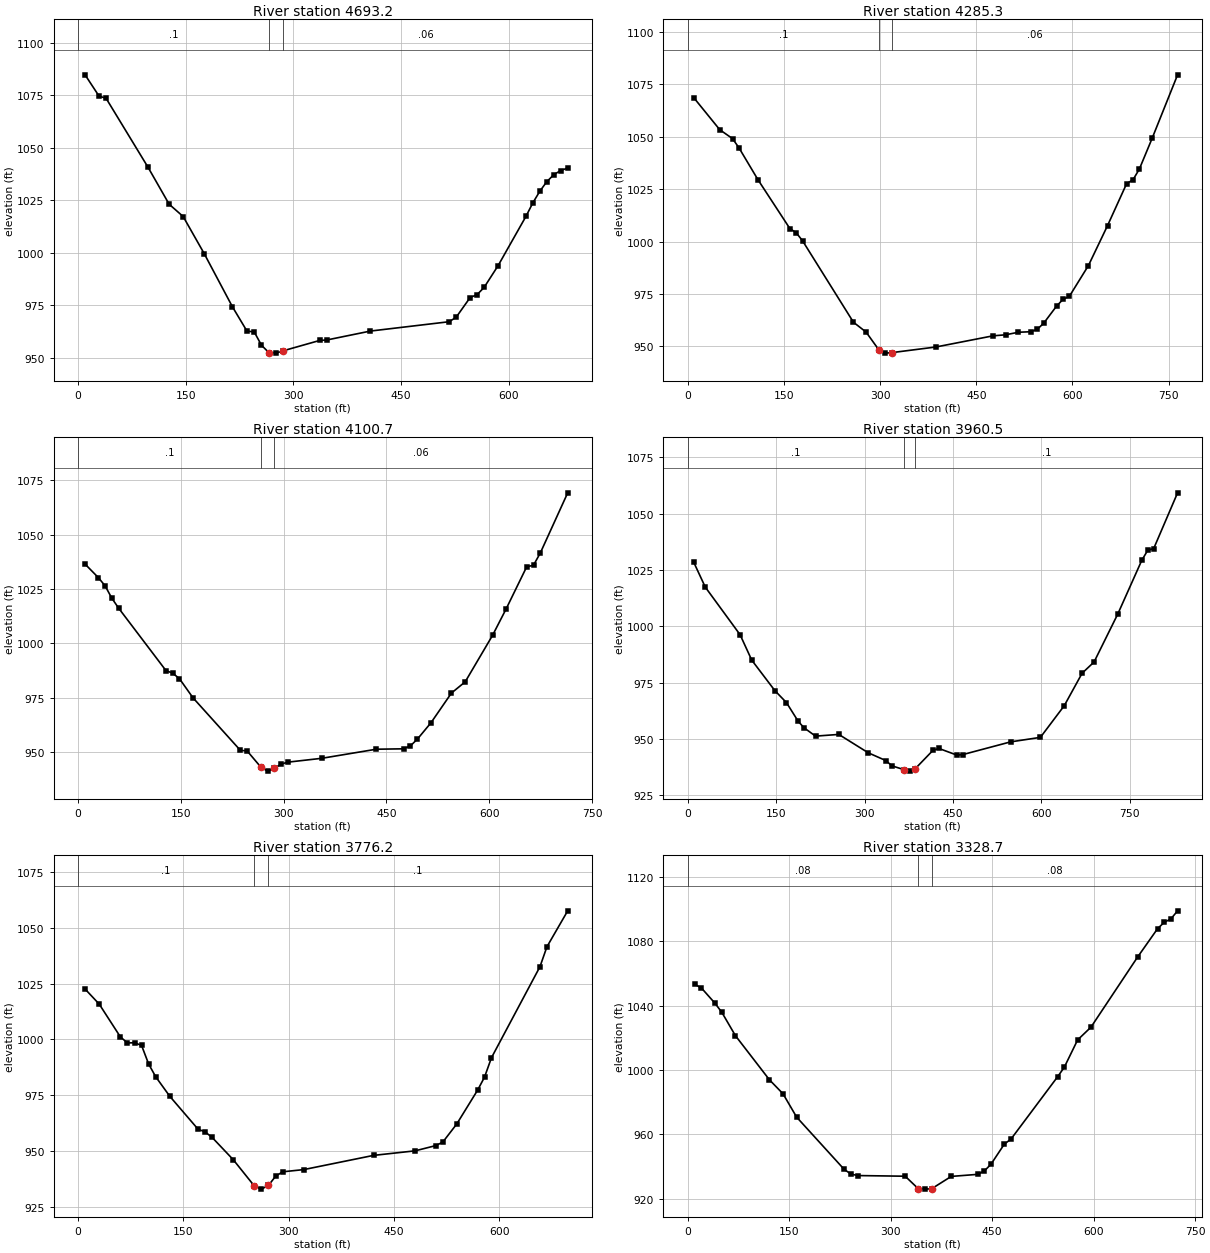
Type RM Length L Ch R = 1 ,4693.2  ,403.9,407.8,411.7
XS GIS Cut Line= 4
     1645074.031      268472.645     1645030.878         268673.
     1644978.478      268941.166     1645049.372      269132.273
#Sta/Elev= 30
     9.8 1084.67    29.3 1074.53      39 1073.55    97.6 1040.65   126.9 1023.14
   146.4  1017.3   175.7  999.67   215.1  974.33   235.3   962.8   245.4  962.42
   255.5  956.08   265.8  952.59   275.8  952.33   285.8  953.45   336.5  958.35
   346.6  958.59   407.3  962.83     517  967.27   526.7  969.42   546.1  978.76
   555.8  980.16   565.5  983.54     585   993.9   623.8 1017.33   633.5 1023.82
   643.2 1029.34   652.9 1033.86   662.6 1037.18   672.3 1039.17     682 1040.36
#Mann= 3 , 0 , 0
       0      .1       0   265.8    .045       0   285.8     .06       0
Bank Sta=265.8,285.8
XS Rating Curve= 0 ,0
Exp/Cntr=0.3,0.1

Type RM Length L Ch R = 1 ,4285.3  ,188.1,184.7,181.2
XS GIS Cut Line= 4
     1644727.264      268409.457     1644650.205      268592.858
     1644556.192      268853.318     1644483.757      269132.273
#Sta/Elev= 30
     9.9 1068.28    49.7 1053.29    69.6 1049.05    79.6  1044.7   109.4 1029.41
   159.1 1006.17   169.1 1004.15     179 1000.28   258.3  961.51     278  956.83
   297.7  948.44   307.7  946.79   317.7  947.01   386.8  949.71   475.8  955.02
   495.7  955.53   515.6  956.74   535.5     957   545.4  958.21   555.3  961.12
   575.2   969.2   585.2  972.41   595.1  973.83   624.9  988.53   654.7 1007.56
   684.5 1027.58   694.5 1029.44   704.4 1034.56   724.3 1049.18     764 1079.45
#Mann= 3 , 0 , 0
       0      .1       0   297.7    .045       0   317.7     .06       0
Bank Sta=297.7,317.7
XS Rating Curve= 0 ,0
Exp/Cntr=0.3,0.1

Type RM Length L Ch R = 1 ,4100.7  ,138.6,140.2,141.8
XS GIS Cut Line= 3
     1644570.063      268438.739     1644446.768      268592.858
      1644409.78      268767.012
#Sta/Elev= 30
     9.9 1036.63    29.6  1030.3    39.5  1026.5    49.3 1020.82    59.2 1016.25
   128.3   987.5   138.2   986.3     148  983.75   167.8  974.96   236.9  950.79
   246.8  950.51   266.5  943.18   276.5  941.23   286.5  942.54   296.3  944.46
   306.2  945.36   355.6  947.13   435.2  951.31   475.1   951.5   485.1   952.9
   495.1  955.93     515  963.49   544.9  977.17   564.9  982.32   604.8 1003.69
   624.7 1015.91   654.6 1035.23   664.6 1035.99   674.6 1041.67   714.5  1069.3
#Mann= 3 , 0 , 0
       0      .1       0   266.5    .045       0   286.5     .06       0
Bank Sta=266.5,286.5
XS Rating Curve= 0 ,0
Exp/Cntr=0.3,0.1

Type RM Length L Ch R = 1 ,3960.5  ,174.8,184.3,193.9
XS GIS Cut Line= 4
      1644548.14      268416.808     1644326.209       268523.15
     1644277.661      268696.534      1644379.38       269088.38
#Sta/Elev= 30
     9.8 1028.53    29.5 1017.43    88.6  996.29   108.3  985.05   147.7  971.46
   167.3  966.17     187  957.95   196.9  955.04   216.6   951.3   256.1  952.06
   306.1   943.9   336.1  940.43   346.1  938.13   366.1  936.47   376.1  935.77
   386.1  936.93   416.1  945.05   426.1  945.82   456.5  942.88   466.6  943.12
   547.6  948.75   598.2  950.75   638.7  964.81     669  979.22   689.3  984.21
   729.8 1005.64   770.3 1029.35   780.4 1033.78   790.5 1034.55     831 1059.27
#Mann= 3 , 0 , 0
       0      .1       0   366.1    .045       0   386.1      .1       0
Bank Sta=366.1,386.1
XS Rating Curve= 0 ,0
Exp/Cntr=0.3,0.1

Type RM Length L Ch R = 1 ,3776.2  ,459.2,447.5,435.6
XS GIS Cut Line= 4
     1644212.508      268332.397     1644160.107      268526.587
     1644056.848      268662.211     1643801.011      268864.107
#Sta/Elev= 30
    10.1 1022.51    30.2 1015.76    60.3  1001.1    70.4  998.38    80.5  998.45
    90.5  997.27   100.6  988.92   110.6  983.24   130.7  974.47     171  959.71
     181  958.52   191.1  956.01   221.2  946.02   251.3  934.21   261.3  932.87
   271.3  934.55   281.4  938.63   291.4  940.63   321.5  941.62     421  947.99
   480.2  950.03   509.9   952.4   519.7  953.99   539.5  962.08   569.1  977.19
     579  983.04   588.9  991.75     658 1032.55   667.9 1041.46   697.5 1057.57
#Mann= 3 , 0 , 0
       0      .1       0   251.3    .045       0   271.3      .1       0
Bank Sta=251.3,271.3
XS Rating Curve= 0 ,0
Exp/Cntr=0.3,0.1

Type RM Length L Ch R = 1 ,3328.7  ,211.7,215.8,220
XS GIS Cut Line= 4
     1643938.176      268054.984     1643756.159       268307.83
     1643734.215      268412.673     1643555.962       268660.67
#Sta/Elev= 30
      10 1053.23    20.1 1050.86    40.2 1041.36    50.2 1035.79    70.3  1021.3
   120.6  993.92   140.7  985.23   160.8  970.77   231.1  938.35   241.2  935.43
   251.2  934.52   321.3  934.11   340.5  926.43   350.5   926.1   360.5  926.35
   389.4  933.99   428.5  935.26   438.4  937.38   448.2  941.56   467.9  954.02
   477.8  957.17   546.7  995.82   556.6 1001.74   576.3 1018.69     596 1026.58
     665 1070.11   694.5 1087.69   704.4 1091.68   714.2 1093.75   724.1 1098.78
#Mann= 3 , 0 , 0
       0     .08       0   340.5    .045       0   360.5     .08       0
Bank Sta=340.5,360.5
XS Rating Curve= 0 ,0
Exp/Cntr=0.3,0.1

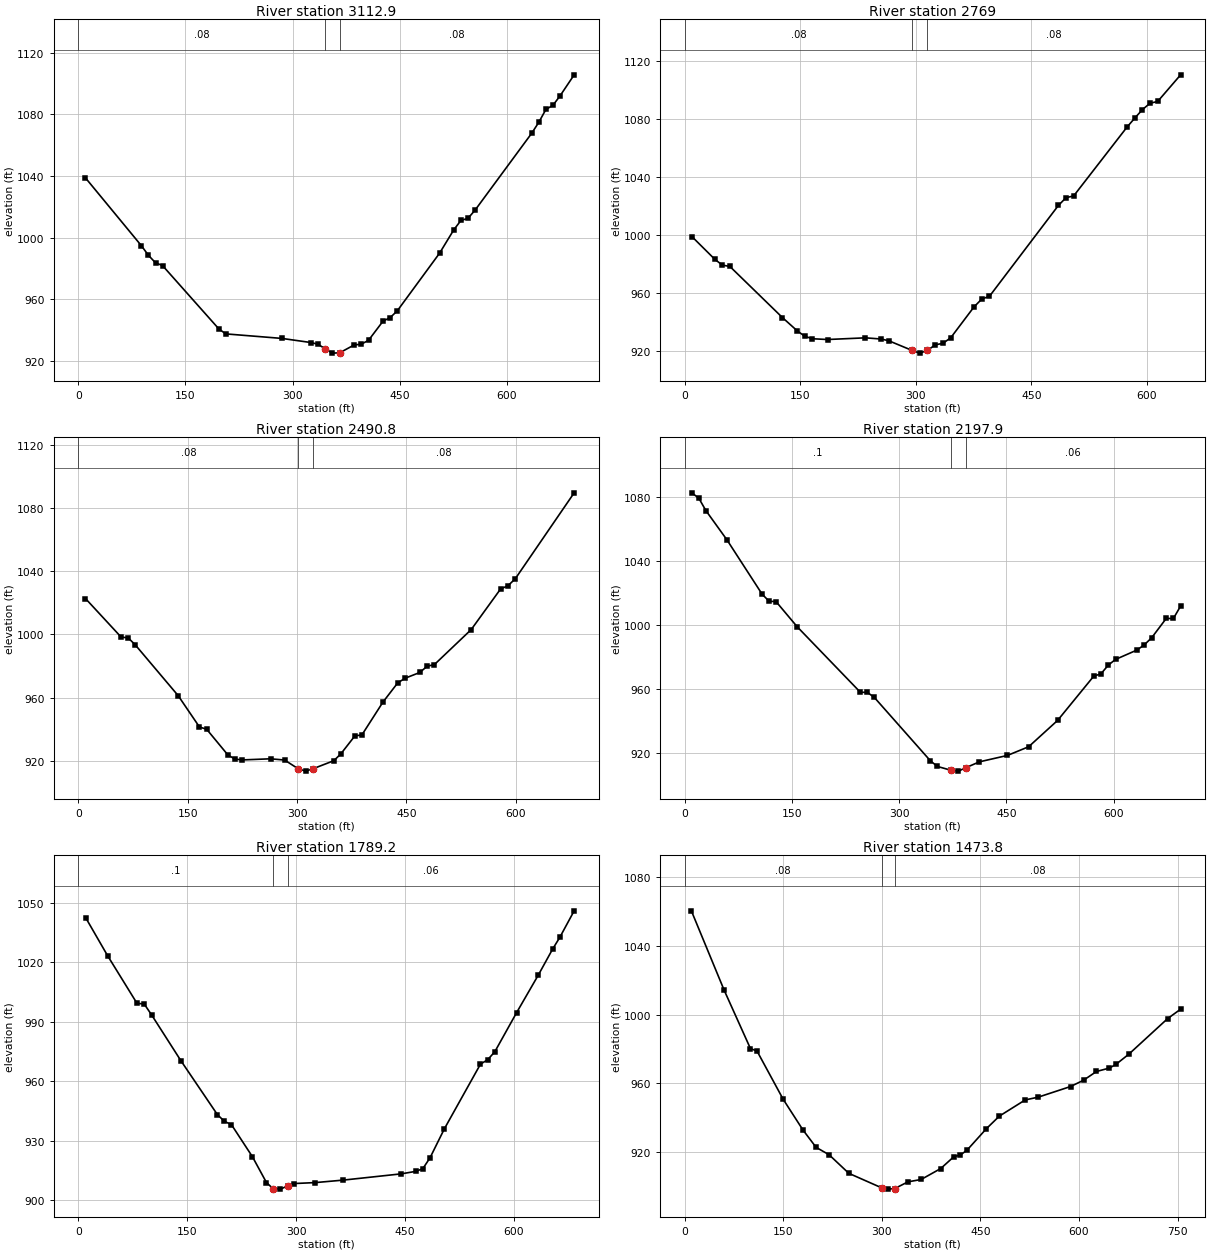
Type RM Length L Ch R = 1 ,3112.9  ,340.1,343.9,347.8
XS GIS Cut Line= 4
     1643714.705      267940.936     1643586.786      268184.443
     1643532.844      268326.232     1643392.596      268554.328
#Sta/Elev= 30
     9.8 1038.82    88.4  994.63    98.2  988.42   108.1  983.58   117.9  981.79
   196.5  940.81   206.3  937.42   285.2  934.47   325.6  931.81   335.7  930.71
     346  927.61     356  924.92     366  925.12   386.3  930.21   396.4  930.74
   406.5  933.26   426.8  945.69   436.7  947.97   446.6  952.29   506.1  989.89
   525.9    1005   535.9 1011.08   545.8 1012.46   555.7 1017.76     635 1067.67
   644.9 1074.76   654.9 1083.14   664.8 1085.85   674.7 1091.95   694.5 1105.63
#Mann= 3 , 0 , 0
       0     .08       0     346    .045       0     366     .08       0
Bank Sta=346,366
XS Rating Curve= 0 ,0
Exp/Cntr=0.3,0.1

Type RM Length L Ch R = 1 ,2769    ,285.7,278.1,270.6
XS GIS Cut Line= 4
     1643395.679      267851.547     1643292.419      268039.572
     1643198.407       268206.02       1643112.1      268427.951
#Sta/Elev= 30
     9.8  998.84      39  983.46    48.8  979.46    58.5  978.57   126.8  943.32
   146.3  934.04     156  930.39   165.8  928.74   185.3  928.21   234.6  929.37
   254.8  928.55   264.8  927.37   295.1  920.69   305.1  918.83   315.1  920.74
   325.2  924.52   335.2   925.6   345.3  929.41   375.5  950.66   385.6  956.09
   395.6     958   485.1 1020.59     495 1025.94   504.9 1027.13   574.3 1074.64
   584.3 1080.79   594.2 1086.61   604.1 1091.01     614 1092.23   643.8 1110.58
#Mann= 3 , 0 , 0
       0     .08       0   295.1    .045       0   315.1     .08       0
Bank Sta=295.1,315.1
XS Rating Curve= 0 ,0
Exp/Cntr=0.3,0.1

Type RM Length L Ch R = 1 ,2490.8  ,296.6,292.9,289.3
XS GIS Cut Line= 4
     1643104.394      267705.134     1643016.547       267933.23
     1642979.558       268102.76      1642968.77      268364.762
#Sta/Elev= 30
     9.8 1022.65    58.7  998.26    68.4  997.76    78.2  993.29   136.9  961.24
   166.2  941.35     176  939.97   205.3  923.61   215.1  921.05   224.9  920.54
   263.7  921.25     283  920.46   301.9  914.86   311.9  913.45   321.9  914.94
   350.5  920.05   360.1  924.35   379.4  935.76     389  936.34   417.9  957.13
   438.1  969.24   448.2  972.22   468.4  975.86   478.5  979.81   488.5  980.87
     539 1003.03   579.3 1028.72   589.4 1030.73   599.5 1035.21   680.2 1089.53
#Mann= 3 , 0 , 0
       0     .08       0   301.9    .045       0   321.9     .08       0
Bank Sta=301.9,321.9
XS Rating Curve= 0 ,0
Exp/Cntr=0.3,0.1

Type RM Length L Ch R = 1 ,2197.9  ,418.5,408.7,399
XS GIS Cut Line= 4
     1642569.603      267611.122     1642723.721      267862.335
     1642711.392      268038.031     1642753.004      268256.879
#Sta/Elev= 30
     9.8 1082.83    19.6 1079.48    29.5 1071.71    58.9 1053.41   108.1 1019.38
   117.9 1014.92   127.7 1014.67   157.2  998.93   245.6  957.89   255.4  957.83
   265.2  954.62   343.6  914.94   353.4  911.41   372.8  908.99   382.8  908.49
   392.8  910.57   412.1  914.31   451.3  918.32     481  923.76   521.5  940.26
   572.1     968   582.2  969.45   592.4  974.89   602.5  978.45   632.9  984.42
     643  987.71   653.1  992.04   673.4 1004.11   683.5 1004.12   693.6  1011.9
#Mann= 3 , 0 , 0
       0      .1       0   372.8    .045       0   392.8     .06       0
Bank Sta=372.8,392.8
XS Rating Curve= 0 ,0
Exp/Cntr=0.3,0.1

Type RM Length L Ch R = 1 ,1789.2  ,300.8,315.4,330
XS GIS Cut Line= 4
     1642239.789      267692.805     1642295.271      267876.206
     1642349.213      268041.113     1642509.496      268315.444
#Sta/Elev= 30
    10.1 1042.64    40.3 1023.42    80.7   999.4    90.8  998.97   100.8  993.57
   141.2  970.38   191.6  943.07   201.2  939.72   210.9  938.02   239.8   921.8
   259.1  908.76   268.4  905.62   278.4  905.46   288.4  907.11   297.6  908.29
   326.6  908.77   365.1  910.03   444.5  913.17   464.4  914.42   474.3  915.75
   484.3  921.28   504.1  935.96   553.8  968.64   563.7  970.85   573.6  974.93
   603.4  994.56   633.2 1013.49   653.1 1026.74     663 1032.67   682.8  1046.1
#Mann= 3 , 0 , 0
       0      .1       0   268.4    .045       0   288.4     .06       0
Bank Sta=268.4,288.4
XS Rating Curve= 0 ,0
Exp/Cntr=0.3,0.1

Type RM Length L Ch R = 1 ,1473.8  ,472.6,469.7,466.8
XS GIS Cut Line= 4
     1642057.929      267749.829     1642051.764      267979.465
     1642002.446      268162.867     1641845.245      268458.775
#Sta/Elev= 30
      10 1060.58    59.9 1014.34    99.9  980.34   109.9   978.9   149.8  950.75
   179.8  932.93   199.8  922.81   219.7  918.44   249.7  907.64   299.7  899.19
   309.7  898.44   319.7   898.8   339.7  902.68   359.7  904.05   389.6  910.45
   409.6  917.36   419.6  918.36   429.5  921.11   459.1  933.68   478.8  940.98
   518.2  950.42   537.9  952.02   587.2  958.22   606.9  961.88   626.6  966.98
   646.3  968.98   656.2  971.11   675.9  977.07     735  997.82   754.7 1003.27
#Mann= 3 , 0 , 0
       0     .08       0   299.7    .045       0   319.7     .08       0
Bank Sta=299.7,319.7
XS Rating Curve= 0 ,0
Exp/Cntr=0.3,0.1

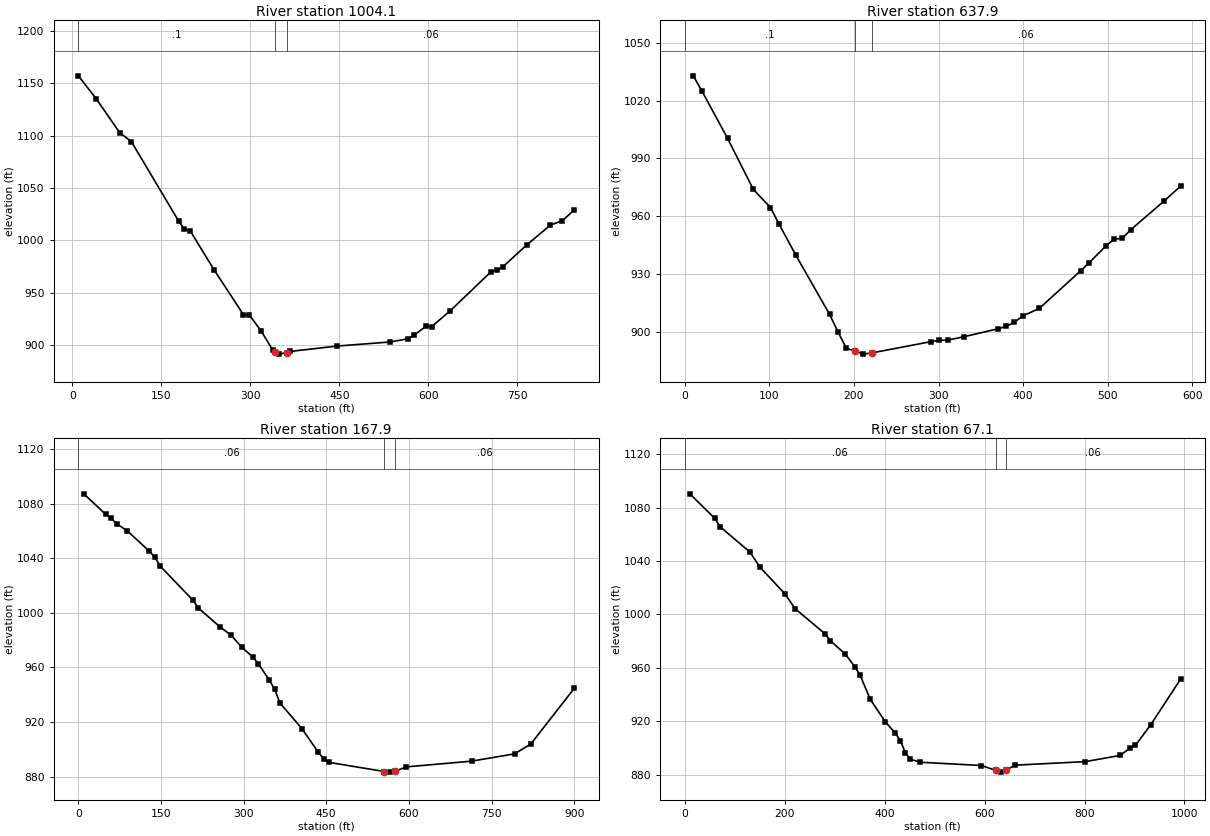
Type RM Length L Ch R = 1 ,1004.1  ,361.3,366.2,371.2
XS GIS Cut Line= 4
     1641603.279      267715.923     1641580.161      267993.336
     1641537.007      268287.703     1641581.702      268554.328
#Sta/Elev= 30
     9.9 1157.03    39.8 1135.39    79.5  1102.9    99.4 1094.19     179  1018.5
   188.9 1010.74   198.8  1008.9   238.6  972.13   288.3  929.14   298.2  928.82
     318  913.77   337.9  895.19  341.66  893.76   347.8  891.42   361.2  892.76
   367.6  894.03     447  899.14   536.2  903.05     566  906.07   575.9  909.24
   595.9  917.92   605.9  917.72     636  932.17   706.1  970.09   716.1  971.43
   726.1  974.83   766.1  995.58   806.2 1014.57   826.2 1018.75   846.2 1028.88
#Mann= 3 , 0 , 0
     9.9      .1       0  341.66    .045       0   361.2     .06       0
Bank Sta=341.66,361.2
XS Rating Curve= 0 ,0
Exp/Cntr=0.3,0.1

Type RM Length L Ch R = 1 ,637.9   ,467.3,470,472.7
XS GIS Cut Line= 4
     1641275.006      267779.111     1641247.265      267886.994
     1641170.205       268102.76      1641137.84      268346.268
#Sta/Elev= 30
    10.1 1032.82    20.3 1024.86    50.6 1000.35      81   973.9   101.3  964.46
   111.4   955.9   131.3  939.72   171.2  909.01   181.1  899.94   191.1  891.33
     201  890.15     211  888.39     221  889.01   290.7  894.83   300.7  895.55
   310.6  895.61   330.5  897.47     370  901.51   379.8  902.76   389.6  904.89
   399.5   908.2   419.1  912.08   468.2  931.72   478.1  935.81   497.7   944.5
   507.5  948.02   517.4  948.52   527.2  952.94   566.5  967.79   586.2  975.58
#Mann= 3 , 0 , 0
       0      .1       0     201    .045       0     221     .06       0
Bank Sta=201,221
XS Rating Curve= 0 ,0
Exp/Cntr=0.3,0.1

Type RM Length L Ch R = 1 ,167.9   ,104.4,100.8,97.2
XS GIS Cut Line= 4
     1641222.606      267637.322     1640837.309      267728.252
     1640737.132      267934.771     1640736.503      268209.359
#Sta/Elev= 30
     9.9 1087.29    49.5 1072.28    59.4 1069.42    69.3 1065.46    89.1 1060.06
   128.7 1045.29   138.6 1041.11   148.5 1034.33   207.8  1009.4   217.7  1003.6
   257.3  989.71   277.1  983.67   296.9  974.77   316.7  967.66   326.6  962.79
   346.4  950.92   356.3  944.06   366.2  933.83   405.9  915.13   435.8  897.67
   445.8  892.66   455.8  890.37   555.5  883.71   565.5  883.27   575.5  884.03
   595.5  887.12   713.7  891.31   792.1  896.69   821.5  903.95     900  944.64
#Mann= 3 , 0 , 0
       0     .06       0   555.5    .045       0   575.5     .06       0
Bank Sta=555.5,575.5
XS Rating Curve= 0 ,0
Exp/Cntr=0.3,0.1

Type RM Length L Ch R = 1 ,67.1    ,70.2,67.1,64
XS GIS Cut Line= 5
     1641221.007      267630.148     1640759.373      267725.726
     1640683.951      267795.296     1640654.692      267887.623
     1640667.696      268208.816
#Sta/Elev= 30
      10 1090.33    60.2 1071.85    70.2 1065.85   130.4 1046.64   150.5 1035.34
   200.6 1015.27   220.7 1004.32   280.8   985.4   290.9  980.37     321  970.32
     341   960.4   351.1  954.26   371.1  936.41   401.2  919.59   421.3  910.97
   431.3  905.49   441.3  896.51   451.4  891.48   471.4  889.23   593.4  886.78
   622.1  883.18   632.1  881.82   642.1  883.17   661.2  887.04   801.5  889.69
   871.8  894.37   891.9  900.13   901.9  901.88   932.1  917.11   992.3  951.52
#Mann= 3 , 0 , 0
       0     .06       0   622.1    .045       0   642.1     .06       0
Bank Sta=622.1,642.1
XS Rating Curve= 0 ,0
Exp/Cntr=0.3,0.1

Chan Stop Cuts=-1
Use User Specified Reach Order=0